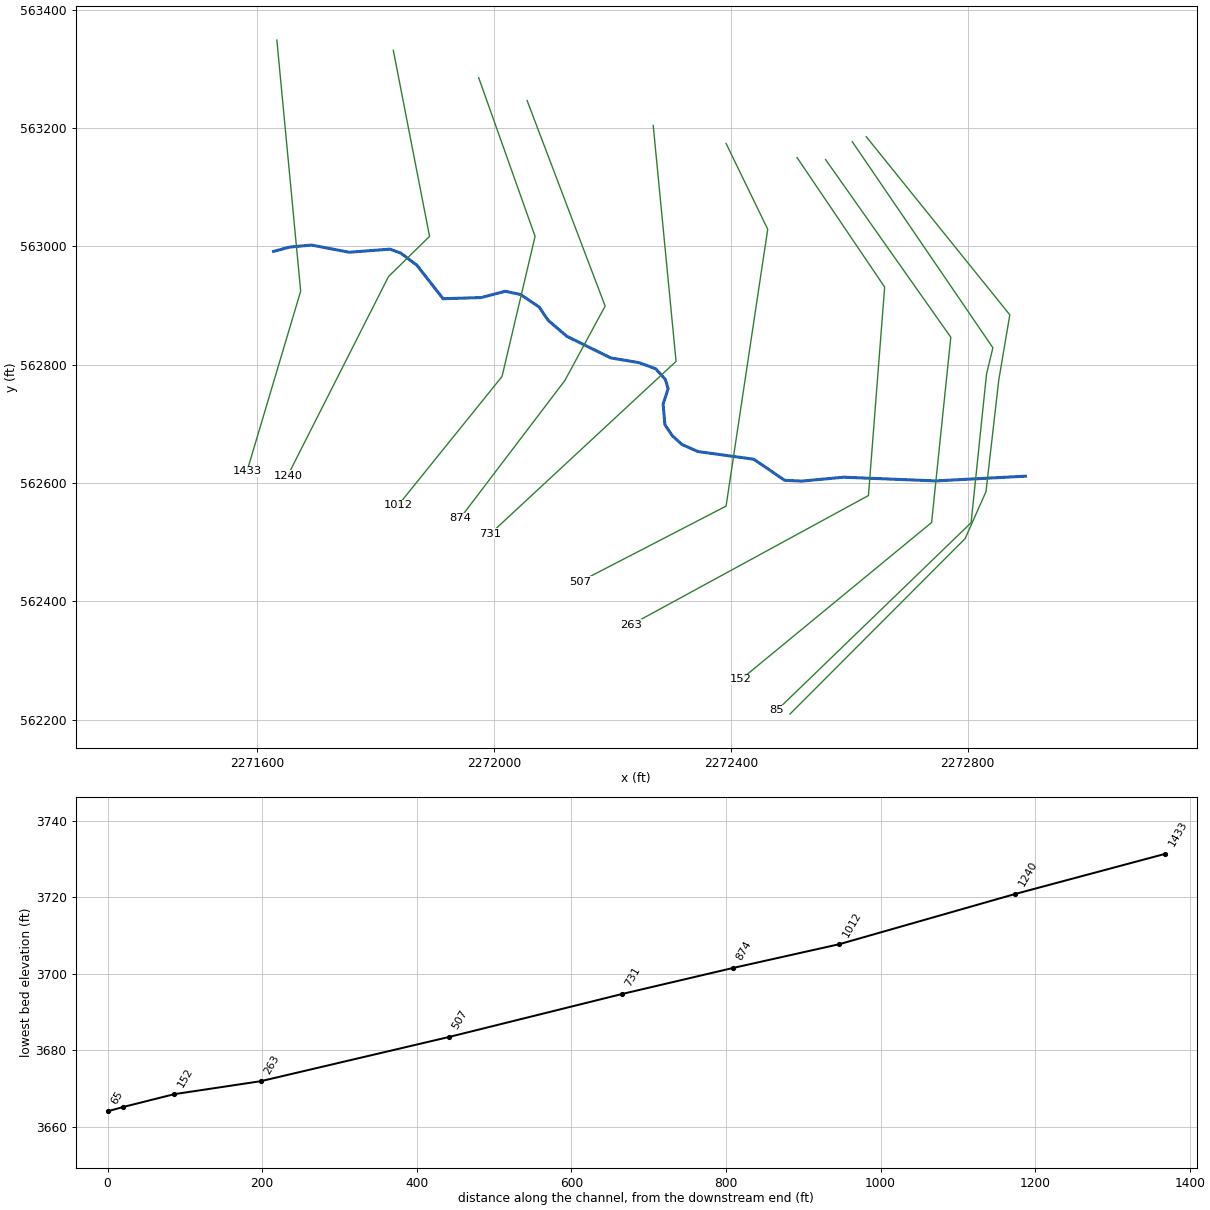
--- BUCKRN.prj (project) ---

Proj Title=BUCKRN
Current Plan=p01
Default Exp/Contr=0,0
English Units
Geom File=g01
Flow File=f01
Plan File=p01
BEGIN DESCRIPTION:
----------MODEL BY WOOD PLC 2022----------
AFH study
Randolph County, WV
HEC-RAS Version: RAS 6.2
Vertical Datum: NAVD88
Projection: NAD 1983 StatePlane West Virginia S FIPS 4702 (US Feet)
Terrain: 1-meter LIDAR (FEMA Region III 3DEP collected 2016-2018)
Land Use: 2019 NLCD
Hydrologic Method:
WV SIR2010-5033 regression equations
Additional Model Notes:
None
END DESCRIPTION:
DSS Export Rating Curves= 0
DSS Export Rating Curve Sorted= 0
DSS Export Volume Flow Curves= 0
DXF OffsetX= 0
DXF OffsetY= 0
DXF ScaleX= 0
DXF ScaleY= 0

--- BUCKRN.p01 (plan) ---

Plan Title=Floodplain
Program Version=6.20
Short Identifier=Floodplain
Geom File=g01
Flow File=f01
Subcritical Flow
K Sum by GR= 0
Std Step Tol= 0.01
Critical Tol= 0.01
Num of Std Step Trials= 20
Max Error Tol= 0.3
Flow Tol Ratio= 0.001
Split Flow NTrial= 30
Split Flow Tol= 0.02
Split Flow Ratio= 0.02
Log Output Level= 0
Friction Slope Method= 1
Unsteady Friction Slope Method= 2
Unsteady Bridges Friction Slope Method= 1
Parabolic Critical Depth
Global Vel Dist= 0 , 0 , 0
Global Log Level= 0
CheckData=True
Encroach Param=-1 ,0,0, 0
Mapping Interval=1HOUR
Computation Time Step Use Courant=        0
Computation Time Step Use Time Series=    0
Computation Time Step Count To Double=0
Computation Time Step Max Doubling=0
Computation Time Step Max Halving=0
Computation Time Step Residence Courant=0
Run HTab= 0
Run UNet= 0
Run Sediment= 0
Run PostProcess= 0
Run WQNet= 0
Run RASMapper=-1
UNET Theta= 0
UNET Theta Warmup= 0
UNET ZTol= 0
UNET ZSATol= 0
UNET MxIter= 0
UNET Max Iter WO Improvement= 0
UNET MaxInSteps= 0
UNET DtIC= 0
UNET DtMin= 0
UNET MaxCRTS= 0
UNET WFStab= 0
UNET SFStab= 0
UNET WFX= 1
UNET SFX= 1
UNET Gravity=32.174
UNET 1D Methodology=Finite Difference
UNET DSS MLevel= 1
UNET Pardiso=0
UNET DZMax Abort= 0
UNET Use Existing IB Tables= 0
UNET Froude Reduction=False
UNET Froude Limit= 0
UNET Froude Power= 0
UNET D1 Cores= 0
UNET WindReference=Eulerian
UNET WindDragFormulation=Hsu (1988)
UNET D2 Coriolis=0
UNET D2 Cores= 0
UNET D2 Theta= 1
UNET D2 Theta Warmup= 1
UNET D2 Z Tol= 0.01
UNET D2 Volume Tol= 0.01
UNET D2 Max Iterations= 20
UNET D2 Equation= 0
UNET D2 RampUpFraction=0.1
UNET D2 TimeSlices= 1
UNET D2 Turbulence Formulation=Non-Conservative (original)
UNET D2 Eddy Viscosity=0.3
UNET D2 Transverse Eddy Viscosity=0.1
UNET D2 Smagorinsky Mixing=0
UNET D2 BCVolumeCheck=0
UNET D2 Cores=0
UNET D2 SolverType=PARDISO (Direct)
UNET D2 Minimum Iterations= 2147483647
UNET D2 Maximum Iterations= 2147483647
UNET D2 Restart Number= 10
UNET D2 Relaxation Coeff=1.3
UNET D2 SOR Precondition Iterations= 10
UNET D2 ILUT Maximum Fill= 8
UNET D2 ILUT Tolerance=1E-08
UNET D1D2 MaxIter= 0
UNET D1D2 ZTol=0.01
UNET D1D2 QTol=0.1
UNET D1D2 MinQTol=1
Write IC File= 0
Write IC File at Fixed DateTime=0
Write IC File at Sim End=0
Echo Input=False
Echo Parameters=False
Echo Output=False
Write Detailed= 0
HDF Write Warmup=0
HDF Write Time Slices=0
HDF Flush=0
HDF Compression= 1
HDF Chunk Size= 1
HDF Spatial Parts= 1
HDF Use Max Rows=0
HDF Fixed Rows= 1
Calibration Method= 0
Calibration Iterations= 20
Calibration Max Change=0.05
Calibration Tolerance=0.2
Calibration Maximum=1.5
Calibration Minimum=0.5
Calibration Optimization Method= 1
WQ AD Non Conservative
WQ ULTIMATE=-1
WQ Max Comp Step=1HOUR
WQ Output Interval=15MIN
WQ Output Selected Increments= 0
WQ Output face flow=0
WQ Output face velocity=0
WQ Output face area=0
WQ Output face dispersion=0
WQ Output cell volume=0
WQ Output cell surface area=0
WQ Output cell continuity=0
WQ Output cumulative cell continuity=0
WQ Output face conc=0
WQ Output face dconc_dx=0
WQ Output face courant=0
WQ Output face peclet=0
WQ Output face adv mass=0
WQ Output face disp mass=0
WQ Output cell mass=0
WQ Output cell source sink temp=0
WQ Output nsm pathways=0
WQ Output nsm derived pathways=0
WQ Create Restart=0
WQ Fixed Restart=0
WQ System Summary=0
WQ Write To DSS=0
Sorting and Armoring Iterations= 10
XS Update Threshold= 0.02
Bed Roughness Predictor= 0
Hydraulics Update Threshold= 0.02
Energy Slope Method= 1
Volume Change Method= 1
Sediment Retention Method= 0
Sediment TS Multiplier= 1
Warm Up Method= 0
XS Weighting Method= 0
Number of US Weighted Cross Sections= 1
Number of DS Weighted Cross Sections= 1
Upstream XS Weight=0
Main XS Weight=1
Downstream XS Weight=0
Number of DS XS's Weighted with US Boundary= 1
Upstream Boundary Weight= 1
Weight of XSs Associated with US Boundary= 0
Number of US XS's Weighted with DS Boundary= 1
Downstream Boundary Weight= 0.5
Weight of XSs Associated with DS Boundary= 0.5
Percentile Method= 0
Sediment Output Level= 3
Mass or Volume Output= 0
Output Increment Type= 1
Profile and TS Output Increment= 1
Transport Output Increment 1
XS Output Flag= 0
XS Output Increment= 10
Read HDF5 Sediment Hotstart= 0
Sediment Hotstart Type= 0
Write Gradation File= 0
Read Gradation Hotstart= 0
Write HDF5 File= 1
Write Binary Output= 1
Write DSS Sediment File= 0
DSS Sediment Output Type= 1
SV Curve= 0
Specific Gage Flag= 0
Subcell Erosion Methods= 0
Subcell Deposition Methods= 0
Advection Scheme= 1
Matrix Solver= 0
Implicit Weighting Factor= 1
Maximum Outer Loop Convergence Iterations= 5
Convergence Maximum Absolute= 0.001
Convergence RMSE= 0.0001
Grain Fractions Max Abs Error= 0.001
Max Subgrid Regions= 1
Max Subgrid Length Scale= 3.402823E+38
Initial Layer Thickness= 3.402823E+38
Min Layer Thickness= 3.402823E+38
Max Layer Thickness= 3.402823E+38
Number of Layers= 5

--- BUCKRN.f01 (steady flow) ---

Flow Title=Flow
Program Version=6.20
Number of Profiles= 1
Profile Names=P100yr
River Rch & RM=BUCKRN,Main            ,1433
     316
Boundary for River Rch & Prof#=BUCKRN,Main            , 1
Up Type= 0
Dn Type= 3
Dn Slope=0.0549
DSS Import GetInterval= 0
DSS Import GetPeak= 0
DSS Import FillOption= 0

--- BUCKRN.g01 (geometry) ---

Geom Title=Geometry
Program Version=6.20

River Reach=BUCKRN          ,Main
Reach XY= 30
      2271627.29      562991.296     2271654.374      562998.588
     2271691.353       563002.06     2271755.068      562989.907
     2271823.991      562995.116     2271842.221      562988.518
     2271869.498      562968.012     2271913.769      562911.371
     2271978.005      562913.324     2272019.021      562923.958
     2272044.411      562918.533     2272076.095      562897.265
     2272091.503      562874.696      2272122.97      562847.786
     2272197.189      562811.328     2272244.932      562803.298
     2272273.144      562792.882     2272288.986      562775.304
     2272293.977      562759.461     2272285.513       562733.42
     2272288.552      562698.263     2272300.704      562680.251
     2272317.197       562665.06     2272344.107      562653.125
     2272438.715      562640.115     2272490.841      562604.524
     2272519.313      562603.136     2272590.841      562609.733
      2272746.05      562603.483      2272897.73      562611.478

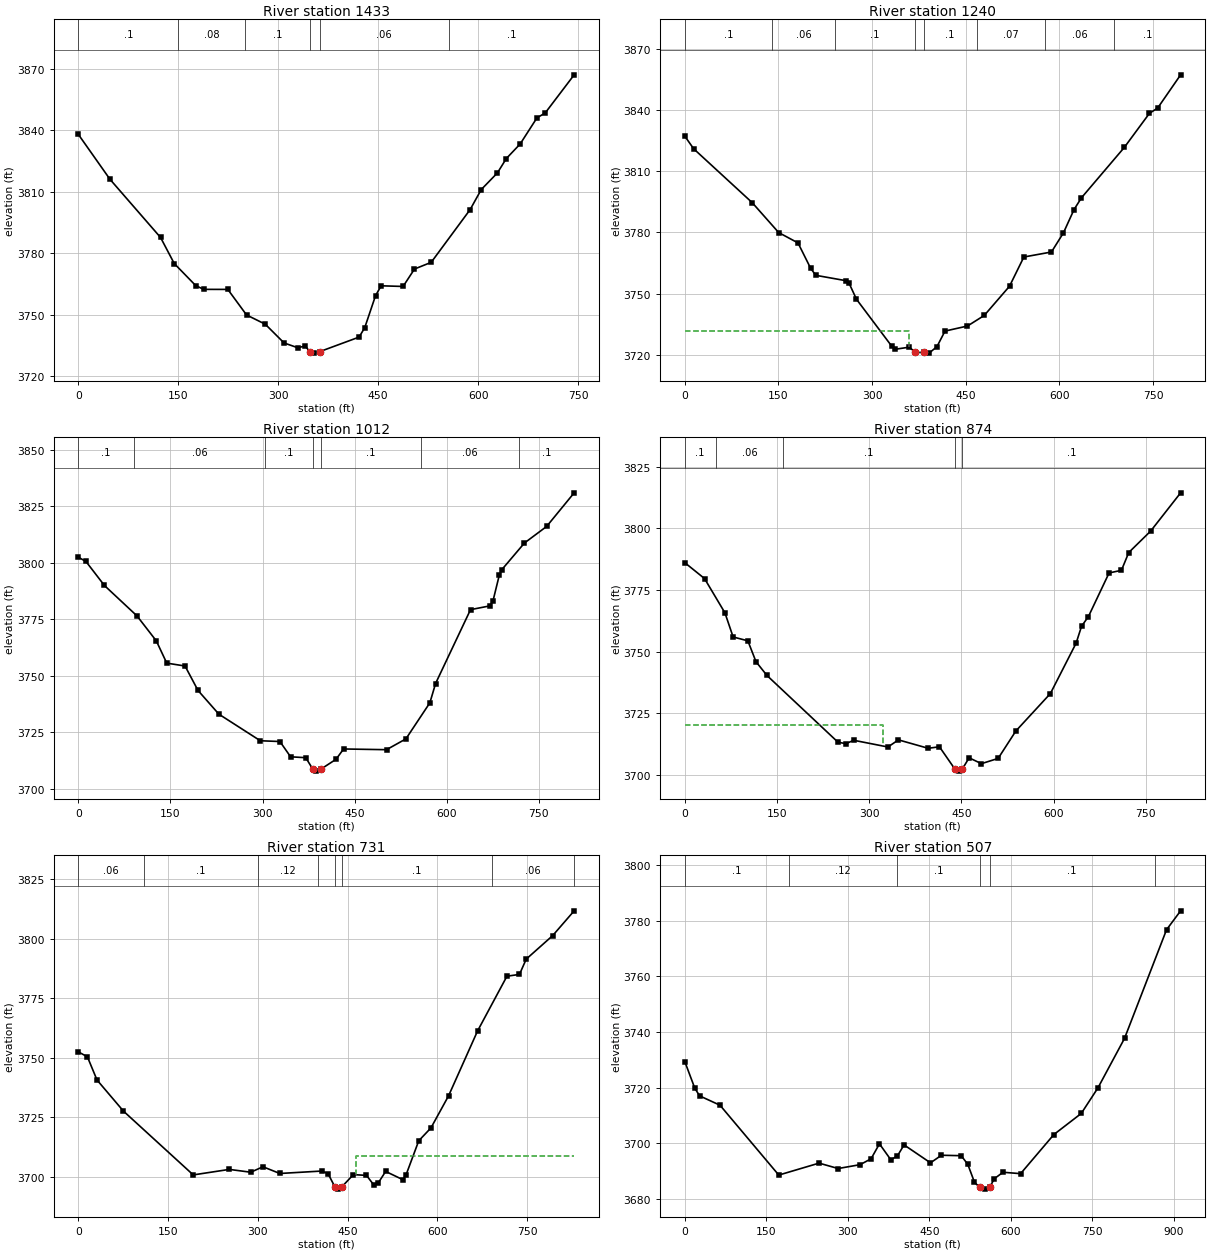
Type RM Length L Ch R = 1 ,1433    ,195.7,193.4,183.5
XS GIS Cut Line= 3
2271632.94407596563348.453238565 2271673.1857496562924.232288179
2271582.43836454562619.606496243
#Sta/Elev= 30
       0 3838.08    47.5 3816.17   123.4 3787.79   143.9  3775.1   176.1 3764.34
   188.1 3762.49   224.3 3762.47   252.4 3750.01   280.5  3745.5   308.7 3736.35
   328.9 3734.06   340.8 3734.83   347.3 3732.01   352.9 3731.39   361.9 3732.08
   421.2  3739.2   429.7 3743.74     446 3759.45   454.4 3764.23   487.3 3763.91
   504.4 3772.41   529.5 3775.68   587.9  3801.4   604.6 3811.18   628.8 3819.28
   642.2 3826.29     663 3833.41   688.1 3846.11   700.6 3848.55     744 3867.13
#Mann= 6 ,-1,0
       0      .1       0     150     .08       0     250      .1       0
   347.3    .045       0   361.9     .06       0  556.13      .1       0
Bank Sta=347.3,361.9
XS Rating Curve= 0 ,0
Exp/Cntr=0.3,0.1

Type RM Length L Ch R = 1 ,1240    ,225.5,227.6,232.2
XS GIS Cut Line= 4
2271829.68331379563331.1259550762271890.92149108 563016.76997831
2271821.51822348562948.7275590962271651.41217545562612.598008181
#Sta/Elev= 30
       0 3827.12    14.2 3820.93   107.9 3794.59   150.4 3779.93   181.3 3774.87
   201.6 3762.43   209.8 3759.01   258.7 3756.35   262.8 3755.36     275 3747.29
   331.1 3724.47   336.8 3722.81   359.7 3723.85  369.353721.258   382.5 3721.25
   391.3 3720.93   403.9 3724.11   416.8 3731.72   452.8  3734.2   479.7 3739.38
   520.1 3753.66   543.1 3767.97   587.3 3770.42   606.5 3779.79   623.5 3791.21
   635.4 3796.97   703.9 3821.56   744.2 3838.26   757.5  3840.9   794.2 3857.12
#Mann= 8 ,-1,0
       0      .1       0     140     .06       0     240      .1       0
  369.35    .045       0   382.5      .1       0  467.46     .07       0
  577.46     .06       0  687.46      .1       0
#XS Ineff= 2 , 0
          359.28 3731.83
Permanent Ineff=
       F       F
Bank Sta=369.35,382.5
XS Rating Curve= 0 ,0
Exp/Cntr(USF)=0,0
Exp/Cntr=0.3,0.1

Type RM Length L Ch R = 1 ,1012    ,138.9,138.1,134.8
XS GIS Cut Line= 4
2271973.93324252563284.8571100112272069.19262942 563016.76997831
2272013.39784567562779.9823594462271837.84840409562562.246617963
#Sta/Elev= 30
       0  3802.5    12.4 3800.62    42.5 3789.98    95.5 3776.52     127 3765.46
     144 3755.61   173.8 3754.33   194.9 3743.51   228.9 3733.01   296.4 3721.24
   328.3  3720.9   345.7 3714.13   370.4 3713.74   381.5 3708.83   386.8 3707.79
  395.723708.788   419.7 3713.03     432  3717.6   501.9 3717.28   533.5 3722.07
   572.5 3738.04   581.8 3746.58   638.7 3779.28   670.1 3780.95   675.3 3783.16
   685.5 3794.47   689.9 3797.06   726.6 3808.81   762.6 3816.11   807.5 3831.01
#Mann= 7 ,-1,0
       0      .1       0      90     .06       0  304.51      .1       0
   381.5    .045       0  395.72      .1       0  557.78     .06       0
  717.78      .1       0
Bank Sta=381.5,395.72
XS Rating Curve= 0 ,0
Exp/Cntr(USF)=0,0
Exp/Cntr=0.3,0.1

Type RM Length L Ch R = 1 ,874     ,144.7,143,140.8
XS GIS Cut Line= 4
2272055.77518245563246.1896762322272187.55813653562898.924516844
2272119.54401964562773.1781175252271942.63372968562540.473043814
#Sta/Elev= 30
       0 3786.11    32.1 3779.66    65.3 3765.75    78.6 3755.97   102.6  3754.4
   115.8 3745.94   133.7 3740.34   249.2 3713.28   262.1 3712.68   274.9 3714.05
   330.5 3711.33   347.6 3714.22   395.9 3710.81   414.3 3711.41   439.4 3702.38
     446 3701.54   451.53702.387   462.6 3706.94   482.6 3704.57   509.8  3706.7
   538.6 3717.81   594.8 3733.01   636.7 3753.48   645.5 3760.31   656.7 3764.25
   690.3 3781.94   710.4    3783   722.3 3790.22   757.9 3798.91   806.7 3814.44
#Mann= 5 ,-1,0
       0      .1       0      50     .06       0     160      .1       0
   439.4    .045       0   451.5      .1       0
#XS Ineff= 2 , 0
          322.02 3720.07
Permanent Ineff=
       F       F
Bank Sta=439.4,451.5
XS Rating Curve= 0 ,0
Exp/Cntr(USF)=0,0
Exp/Cntr=0.3,0.1

Type RM Length L Ch R = 1 ,731     ,220.2,224.2,232.5
XS GIS Cut Line= 3
2272268.77888398563204.2692846452272307.36987541562805.465905267
2271993.88751036562514.319153819
#Sta/Elev= 30
       0  3752.5    15.2 3750.38    31.2 3740.65    75.4 3727.56     192 3700.74
   252.3 3703.05   288.1 3701.87   308.5 3704.16   336.7 3701.34     407 3702.37
   417.3 3701.26   428.6 3695.74   434.3 3694.76   440.53695.778   459.6 3700.86
   481.5 3700.54   493.7 3696.51     501  3697.3   513.5 3702.21   542.2 3698.74
   547.5 3700.67   568.8 3715.09   589.2  3720.5   618.6 3733.97   667.1 3761.28
   716.2  3784.3   737.1 3785.05   748.4 3791.48   792.6 3801.37   828.5 3811.79
#Mann= 8 ,-1,0
       0     .06       0     110      .1       0     300     .12       0
     400      .1       0   428.6    .045       0   440.5      .1       0
  690.67     .06       0   828.5      .1       0
#XS Ineff= 2 , 0
                          464.68          3708.8
Permanent Ineff=
       F       F
Bank Sta=428.6,440.5
XS Rating Curve= 0 ,0
Exp/Cntr(USF)=0,0
Exp/Cntr=0.3,0.1

Type RM Length L Ch R = 1 ,507     ,242.1,243.2,243
XS GIS Cut Line= 4
2272391.89254048563173.7405258282272462.22180231563028.776128998
2272391.89254048562560.8712441792272145.02247855562433.130340042
#Sta/Elev= 30
       0 3729.33    18.4 3719.75    27.3    3717    64.8 3713.64   172.9 3688.55
     247 3692.84   282.1  3690.9   322.5 3692.29   342.7  3694.4   358.1 3699.77
   379.1 3694.03   391.3 3695.48   403.4 3699.39     452 3692.95   472.2 3695.67
   508.6 3695.51   520.7 3692.38   532.9 3685.98   542.3 3684.15   553.1  3683.5
   561.2 3684.23   569.3 3687.22   585.4 3689.56   617.8 3689.06     679 3703.11
   729.4 3710.69   760.1 3719.88     809 3737.66   886.3  3776.7   912.2 3783.48
#Mann= 6 ,-1,0
       0      .1       0  191.12     .12       0  391.12      .1       0
   542.3    .045       0   561.2      .1       0  864.28     .06       0
Bank Sta=542.3,561.2
XS Rating Curve= 0 ,0
Exp/Cntr(USF)=0,0
Exp/Cntr=0.3,0.1

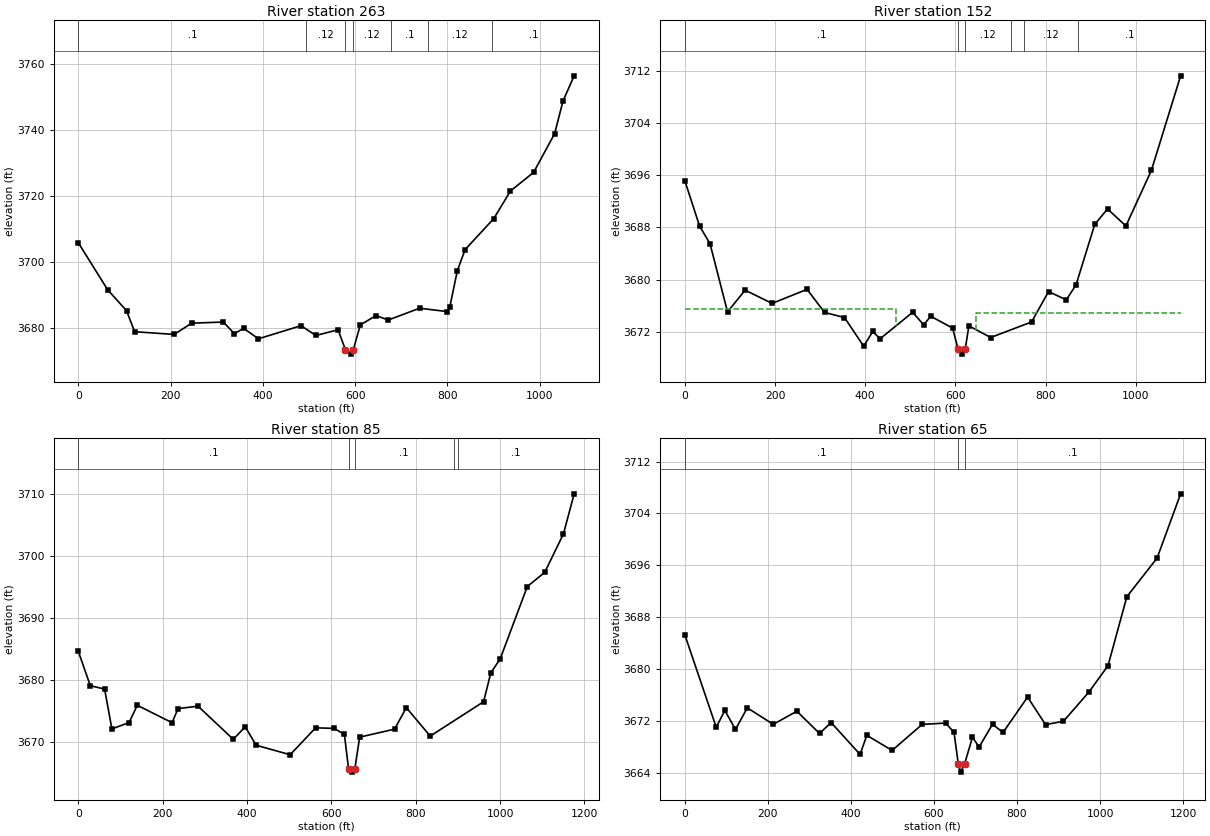
Type RM Length L Ch R = 1 ,263     ,111.9,111.8,111.5
XS GIS Cut Line= 4
2272511.84056768563149.877109799 2272659.8008282  562931.0365301
2272632.40676642 562578.741054292272231.03941911562360.129821249
#Sta/Elev= 30
       0 3705.76    63.6 3691.49   104.5 3685.13     122 3678.76   207.7 3677.93
   245.6 3681.35   314.2 3681.69   338.2 3678.17   358.3 3679.77   390.4 3676.61
   482.7 3680.59   514.6 3677.61   562.9 3679.34     579 3673.24     591 3671.95
  595.833673.209   611.1 3680.82   645.1 3683.64   671.9 3682.32   739.7 3685.89
     800 3684.86   804.8 3686.12   821.5 3697.32   838.2 3703.69   900.2 3713.07
   936.6  3721.5   986.7 3727.13  1032.3  3738.9  1050.5 3748.86  1074.6 3756.46
#Mann= 7 ,-1,0
       0      .1       0  494.17     .12       0     579    .045       0
  595.83     .12       0  677.52      .1       0  757.52     .12       0
  897.52      .1       0
Bank Sta=579,595.83
XS Rating Curve= 0 ,0
Exp/Cntr(USF)=0,0
Exp/Cntr=0.3,0.1

Type RM Length L Ch R = 1 ,152     ,67,67,67.2
XS GIS Cut Line= 4
2272559.99238711563146.5905349252272771.56157383  562846.2636752
 2272739.1072826562533.1616005852272417.14245635562268.042585542
#Sta/Elev= 30
       0 3695.19    32.7 3688.22    55.9 3685.51    94.7 3675.05   133.8 3678.38
   193.5 3676.34     271  3678.5     310 3674.95     354 3674.18   396.6 3669.77
   416.7 3672.04   432.8 3670.91   505.2 3674.98   529.3 3673.07   545.4 3674.36
   593.7 3672.56   605.7 3669.35   613.8 3668.56   621.8 3669.38   629.8  3672.9
   678.1 3671.11   768.8  3673.5   806.4 3678.16   845.7 3676.89   867.3 3679.18
   908.8 3688.46   937.1 3690.84   977.9 3688.23  1034.5 3696.78  1099.2 3711.27
#Mann= 6 ,-1,0
       0      .1       0   605.7    .045       0   621.8     .12       0
  722.15      .1       0  752.15     .12       0  872.15      .1       0
#XS Ineff= 2 , 0
          467.87 3675.55  646.35         3674.93
Permanent Ineff=
       F       F
Bank Sta=605.7,621.8
XS Rating Curve= 0 ,0
Exp/Cntr=0.3,0.1

Type RM Length L Ch R = 1 ,85      ,19.8,19.4,20
XS GIS Cut Line= 5
2272605.10984854563176.6693144732272842.62983979562828.466203179
2272831.87044699562783.8360307942272805.82985025562532.817171464
2272477.96747911562215.949887024
#Sta/Elev= 30
       0 3684.59    28.4 3679.07    62.3 3678.53    79.6 3672.11   120.4 3673.14
   139.8 3675.92   222.1 3673.12   236.6 3675.39   283.9 3675.77   367.4 3670.44
   395.8 3672.46   421.5 3669.49   502.3 3667.96   562.6 3672.29   606.8  3672.2
   630.9 3671.22   640.8 3665.67   648.1 3665.16   655.6 3665.67   667.1 3670.79
   749.9 3672.08   777.7 3675.54   834.4 3670.96     961 3676.49     978 3681.13
  1000.2 3683.37  1064.6 3695.03  1105.9 3697.31  1150.4 3703.52  1175.7 3709.95
#Mann= 5 ,-1,0
       0      .1       0   640.8    .045       0   655.6      .1       0
  889.77     .12       0  899.77      .1       0
Bank Sta=640.8,655.6
XS Rating Curve= 0 ,0
Exp/Cntr=0.3,0.1

Type RM Length L Ch R = 1 ,65      ,,,
XS GIS Cut Line= 6
2272628.65946241563185.2224317082272871.23583441562884.167017967
2272852.65796428562774.3519264942272830.98109661562585.271755611
2272795.74055916562505.9805463412272499.86236629562209.510392614
#Sta/Elev= 30
       0 3685.28    75.7 3670.99    96.4 3673.59     122 3670.66   150.5 3673.99
     213 3671.45   269.9 3673.47   324.4 3670.04   352.4 3671.72   422.1  3666.8
   438.3 3669.75   499.2 3667.42   571.7 3671.44   628.2 3671.64   648.3  3670.2
  658.51  3665.4   664.4 3664.07     674 3665.39   692.8 3669.46   708.7 3667.94
     741 3671.46   766.3 3670.19   825.5 3675.65   868.7  3671.4   911.9 3671.92
     974  3676.5  1019.2 3680.51  1064.5 3691.15  1137.4 3697.12    1194 3707.03
#Mann= 3 ,0,0
       0      .1       0  658.51    .045       0     674      .1       0
Bank Sta=658.51,674
XS Rating Curve= 0 ,0
Exp/Cntr(USF)=0,0
Exp/Cntr=0.3,0.1
LCMann Table=0

Chan Stop Cuts=-1
Use User Specified Reach Order=0
Composite Channel Slope=5